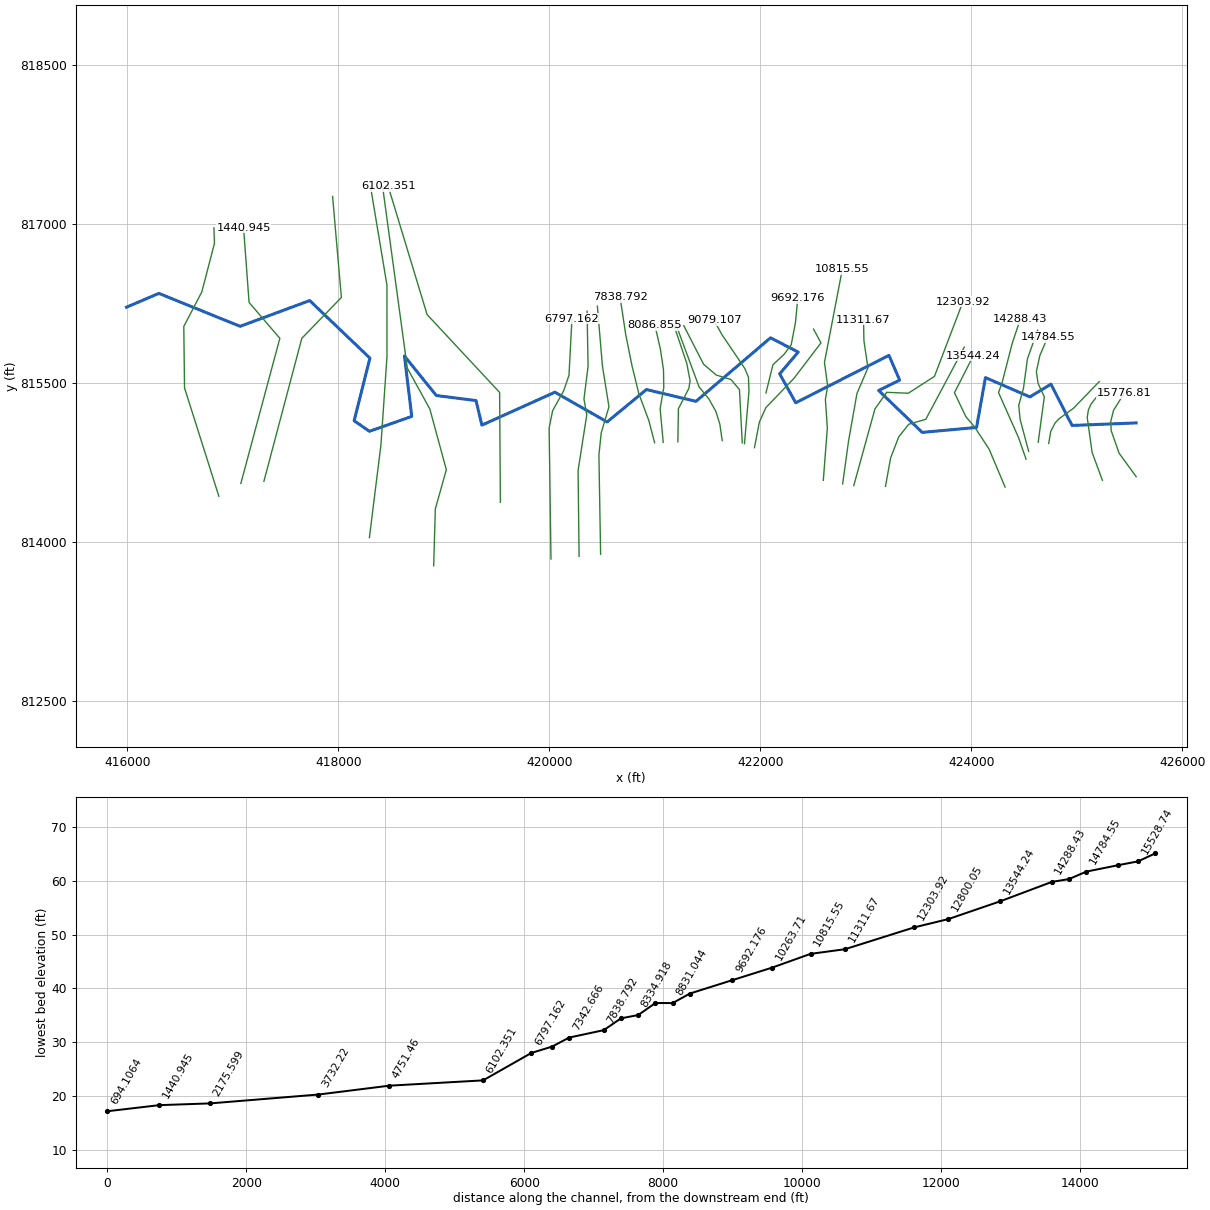
--- 5893_ras.prj (project) ---

Proj Title=5893
Current Plan=p01
Default Exp/Contr=0.3,0.1
English Units
Geom File=g01
Flow File=f01
Plan File=p01
Y Axis Title=Elevation
X Axis Title(PF)=Main Channel Distance
X Axis Title(XS)=Station
BEGIN DESCRIPTION:
RFD model 5893 exported to HEC-RAS
END DESCRIPTION:

--- 5893_ras.p01 (plan) ---

Plan Title=Plan 01
Program Version=4.10
Short Identifier=Plan 01
Geom File=g01
Flow File=f01
Subcritical Flow
Calc Critical at every XS
Secant Critical Depth

--- 5893_ras.f01 (steady flow) ---

Flow Title=Flow 01
Program Version=5.01
Number of Profiles= 6
Profile Names=10yr,25yr,50yr,100yr,100plus,500yr
River Rch & RM=5893,28,15776.81
 7364.4511644.7215650.7719164.3527979.9527888.41
River Rch & RM=5893,28,15528.74
 7402.7611708.7915740.0419277.05 28144.528040.04
River Rch & RM=5893,28,15248.06
 7404.8411712.2715744.8819283.15 28153.428048.23
River Rch & RM=5893,28,14784.55
 7419.0711736.1115778.1319325.1728214.7428104.83
River Rch & RM=5893,28,14536.49
 7419.9311737.5615780.14 19327.728218.4528108.24
River Rch & RM=5893,28,14288.43
 7440.7811772.5215828.9219389.3628308.4728191.35
River Rch & RM=5893,28,13544.24
 7480.6111838.8415921.0819505.4428477.9528346.42
River Rch & RM=5893,28,12800.05
 7489.2111853.2215941.1219530.7328514.8728380.38
River Rch & RM=5893,28,12303.92
 7491.7711857.5215947.11 19538.328525.9328390.57
River Rch & RM=5893,28,11311.67
  7517.711901.0716007.9419615.2728638.2928494.38
River Rch & RM=5893,28,10815.55
 7558.9511970.0416104.0219736.5428815.3528656.92
River Rch & RM=5893,28,10263.71
 7563.1911977.1616113.95 19749.128833.6928673.83
River Rch & RM=5893,28,9692.176
 7584.9512013.7416165.0619813.7928928.1328761.03
River Rch & RM=5893,28,9079.107
 7589.9412022.1516176.8619828.7528949.9828781.29
River Rch & RM=5893,28,8831.044
 7601.6912041.9316204.5119863.7829001.1128828.55
River Rch & RM=5893,28,8582.981
 7603.0212044.1816207.6619867.7729006.9428833.95
River Rch & RM=5893,28,8334.918
  7606.212049.5316215.1519877.26 29020.828846.77
River Rch & RM=5893,28,8086.855
 7608.3712053.1916220.2819883.7529030.2828855.54
River Rch & RM=5893,28,7838.792
 7636.5912100.8316287.0219968.4229153.8928970.14
River Rch & RM=5893,28,7342.666
 7638.7312104.4616292.1119974.8829163.32 28978.9
River Rch & RM=5893,28,7094.603
 7866.8712483.25 16817.620635.8330128.3129853.39
River Rch & RM=5893,28,6797.162
  7873.4 12494.316833.1220655.5330157.0829880.01
River Rch & RM=5893,28,6102.351
 7878.4612502.8816845.1420670.8130179.3829900.64
River Rch & RM=5893,28, 4751.46
 7979.34 12672.617082.4820971.3930618.2330303.41
Boundary for River Rch & Prof#=5893,28,1
Up Type= 0
Dn Type= 2
Boundary for River Rch & Prof#=5893,28,2
Up Type= 0
Dn Type= 2
Boundary for River Rch & Prof#=5893,28,2
Up Type= 0
Dn Type= 2
Boundary for River Rch & Prof#=5893,28,2
Up Type= 0
Dn Type= 2
Boundary for River Rch & Prof#=5893,28,2
Up Type= 0
Dn Type= 2
Boundary for River Rch & Prof#=5893,28,2
Up Type= 0
Dn Type= 2

--- 5893_ras.g01 (geometry) ---

Geom Title=5893
Program Version=4.10

River Reach=5893,28
Reach XY= 30
425563.878531545815124.434799373424955.958743215815100.539666221
  424756.4448542815490.122999594424556.722631991815369.845221803
424135.055965483815552.067444041424051.167076468815081.789666221
423535.889298767815035.122999579423122.486521095815430.539666265
423322.236520886815527.872999549423220.569854319815761.622999564
422336.819854438815314.539666221422184.597631991815587.456332907
422360.708743155815792.456332922422097.930965543815927.456332907
421391.542076439815328.150777355420921.542076766815439.261888474
  420549.3198542815133.706332907 420054.31985423815414.261888474
419362.097631991815103.706332937419305.986521095815335.372999609
418929.832164824815382.975658104418627.748831511815756.239546984
418697.193276078815185.927047029418296.151609391815045.302046999
418150.904903054815145.252805248418300.673375368815735.740582749
417729.537182063 816278.67988725417070.324063182816035.602972895
416300.358785182 816346.36686179415992.332172036816216.158528462

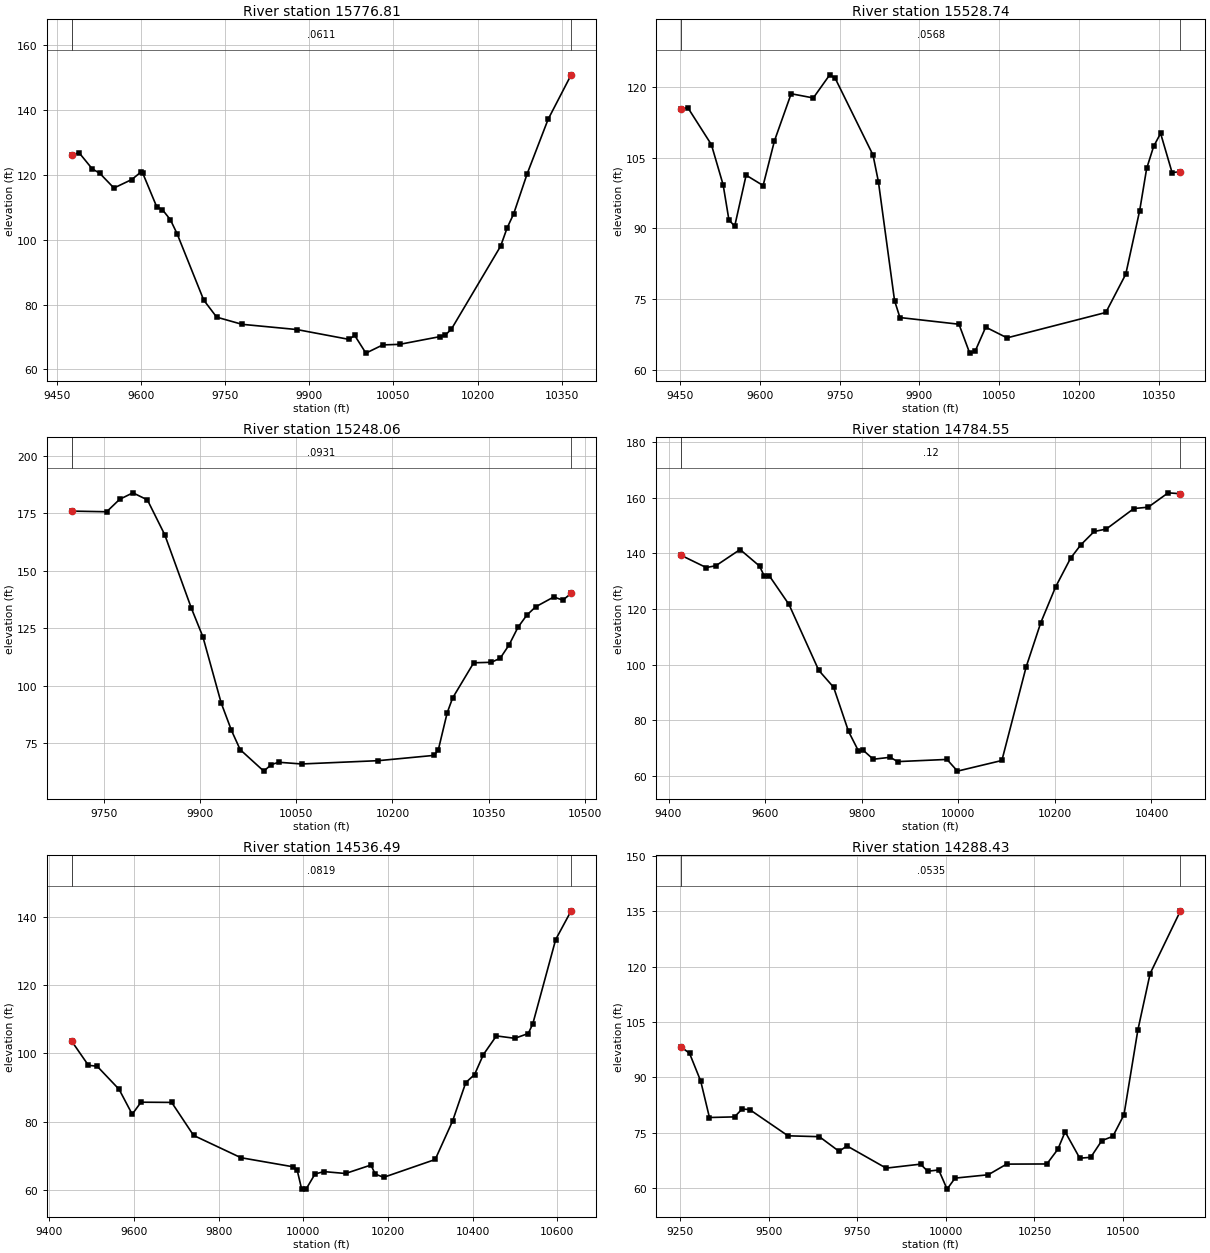
Type RM Length L Ch R = 1 ,15776.81,248.062900,248.062900,248.062900
XS GIS Cut Line= 6
425563.882989369814617.434010719425401.988996363814839.356016749
425326.817892739815052.808358452425323.579264582815140.291214015
425349.810877814815244.377291877 425452.68761069815406.625671822
#Sta/Elev= 30
9475.909126.20859489.297126.76569512.756121.80079525.836120.49559551.329115.9198
9583.181118.52889599.107120.77369602.895120.44239627.658110.13469637.919109.2258
 9651.97106.16529663.965101.85969711.51681.383139734.64276.11873 9779.8573.91407
9877.61472.300769970.67569.273469980.81270.5031310000.8565.0330110030.9167.56291
10060.9467.7377810132.3170.1003110142.8170.6634610153.3872.4292710241.2398.01085
10252.71 103.59710264.35107.912410288.51120.289810325.92137.102310367.01150.8016
#Mann= 3 , 0 , 0
9475.909  0.0611       09475.909  0.0611       010367.01  0.0611       0
#XS Ineff= 2 , 0
       0                               0
Bank Sta=9475.909,10367.01
Exp/Cntr=0.3,0.1

Type RM Length L Ch R = 1 ,15528.74,280.687500,280.687500,280.687500
XS GIS Cut Line= 6
425243.859880733814583.256785521425146.462535634814846.044464136
425100.002030936815176.192676978425111.568741737815249.437432554
425138.550249411815305.953324601425255.892681211815451.990881586
#Sta/Elev= 30
9451.605115.28159464.612115.58349508.914 107.7469530.99899.230439541.84191.81706
9552.68490.442619574.205101.27259606.174  99.0799627.487108.54829658.911118.5375
9700.537117.64479731.483122.54589741.672121.8292 9812.89105.53669823.05599.86605
9853.35574.695769863.45571.098399974.557 69.67899994.70663.5545110004.7363.90012
10024.8169.0616610064.9766.7910210250.7372.1705110288.1880.27902 10314.493.78021
10327.51102.690110340.62107.377810353.74110.1389 10375.3101.835110391.05101.9892
#Mann= 3 , 0 , 0
9451.605  0.0568       09451.605  0.0568       010391.05  0.0568       0
#XS Ineff= 2 , 0
       0                               0
Bank Sta=9451.605,10391.05
Exp/Cntr=0.3,0.1

Type RM Length L Ch R = 1 ,15248.06,463.501300,463.501300,463.501300
XS GIS Cut Line= 6
424734.838783434814930.579986179424754.405480838815045.206364536
424796.026384026815124.804270689424833.673653125815164.378032618
424970.754453199815263.517282503425213.746362249815514.166830487
#Sta/Elev= 30
9698.903 175.9439753.577175.66659773.913181.0858  9794.6183.89969817.166180.8389
9844.286165.69579885.908133.71589903.888121.3017  9932.492.561969948.57680.53073
9962.11372.206549999.00662.8607110010.7365.7081510022.4566.7142210058.1765.97536
10178.1767.4136910264.96  69.71210271.62 72.153510285.4388.2084210293.9594.67753
10326.86 109.97910354.48110.195310368.29 111.97710382.11117.742910395.92125.3751
10409.73130.676110423.54134.305410451.89138.601310466.07137.234310479.07140.1588
#Mann= 3 , 0 , 0
9698.903  0.0931       09698.903  0.0931       010479.07  0.0931       0
#XS Ineff= 2 , 0
       0                               0
Bank Sta=9698.903,10479.07
Exp/Cntr=0.3,0.1

Type RM Length L Ch R = 1 ,14784.55,248.062900,248.062900,248.062900
XS GIS Cut Line= 6
424635.182309958814942.733510296424693.421165352815370.123660028
424634.014973147815497.571650927424618.252546656815608.294145412
 424650.86580559 815760.06131824424726.546243327815934.950671474
#Sta/Elev= 30
9425.731139.33559478.077134.89899498.079135.55549548.194141.38519588.502135.4341
9598.603131.70199608.705131.93769649.457121.61639711.07997.927269741.89791.81807
9772.71575.96288 9793.2668.925179803.53369.114519823.87265.931359859.17266.64133
 9874.2765.079929976.52265.867469998.28861.6564410090.2565.4863910140.3699.06221
10170.76115.054310201.45127.917810232.58138.275210253.48143.033710281.35147.8727
10306.38148.753710363.55156.132310393.22156.618710434.55161.785210459.96 161.453
#Mann= 3 , 0 , 0
9425.731    0.12       09425.731    0.12       010459.96    0.12       0
#XS Ineff= 2 , 0
       0                               0
Bank Sta=9425.731,10459.96
Exp/Cntr=0.3,0.1

Type RM Length L Ch R = 1 ,14536.49,248.063000,248.063000,248.063000
XS GIS Cut Line= 6
424544.749239107814856.813422333424463.829433981815158.141373112
424450.843507773 815290.05274937424495.812970252815452.176256635
424533.633105299815729.997849746424629.598533763815998.339558495
#Sta/Elev= 30
9452.475103.61949492.01496.537299512.72396.262189564.49489.506549595.55782.19568
9616.26685.730499688.74685.668779740.517 76.00659852.45469.472579974.47666.83997
9985.01865.95119 9995.5660.4014210006.1860.2751910027.4264.7060710048.4265.40555
10099.4164.8534610159.5667.3315410169.59 64.670410189.6463.7379810311.2968.95603
10352.28 80.197710383.4791.4753710404.2793.8259910425.0699.6688910455.83105.1445
10499.25104.436710531.08 105.84110541.81108.677510595.88133.359510632.42 141.769
#Mann= 3 , 0 , 0
9452.475  0.0819       09452.475  0.0819       010632.42  0.0819       0
#XS Ineff= 2 , 0
       0                10249.74       0
Bank Sta=9452.475,10632.42
Exp/Cntr=0.3,0.1

Type RM Length L Ch R = 1 ,14288.43,744.188800,744.188800,744.188800
XS GIS Cut Line= 6
  424520.0811328 814781.92809957424449.275342562814985.299445961
424259.442550825815410.466462058424294.107305943815508.116835564
 424390.59447337815880.858960876 424466.57411136816104.932450064
#Sta/Elev= 30
9252.724 98.28589277.00796.543359308.58188.995779333.15879.148719403.92779.31801
 9425.2181.442679446.49481.307959554.76774.192519643.33273.954659698.90869.98644
9721.13871.45498 9831.6565.439369928.71566.51714 9948.8364.592939979.97964.94482
10003.5759.7511610026.1162.7346410119.7663.6403110171.5166.5286910285.0666.56443
10316.01 70.534110336.64 75.276710377.9168.1363610408.8668.3599710439.9872.87515
 10471.374.0521710502.6279.8861810541.75102.804310576.39118.120310661.94135.1273
#Mann= 3 , 0 , 0
9252.724  0.0535       09252.724  0.0535       010661.94  0.0535       0
#XS Ineff= 2 , 0
       0                10200.51       0
Bank Sta=9252.724,10661.94
Exp/Cntr=0.3,0.1

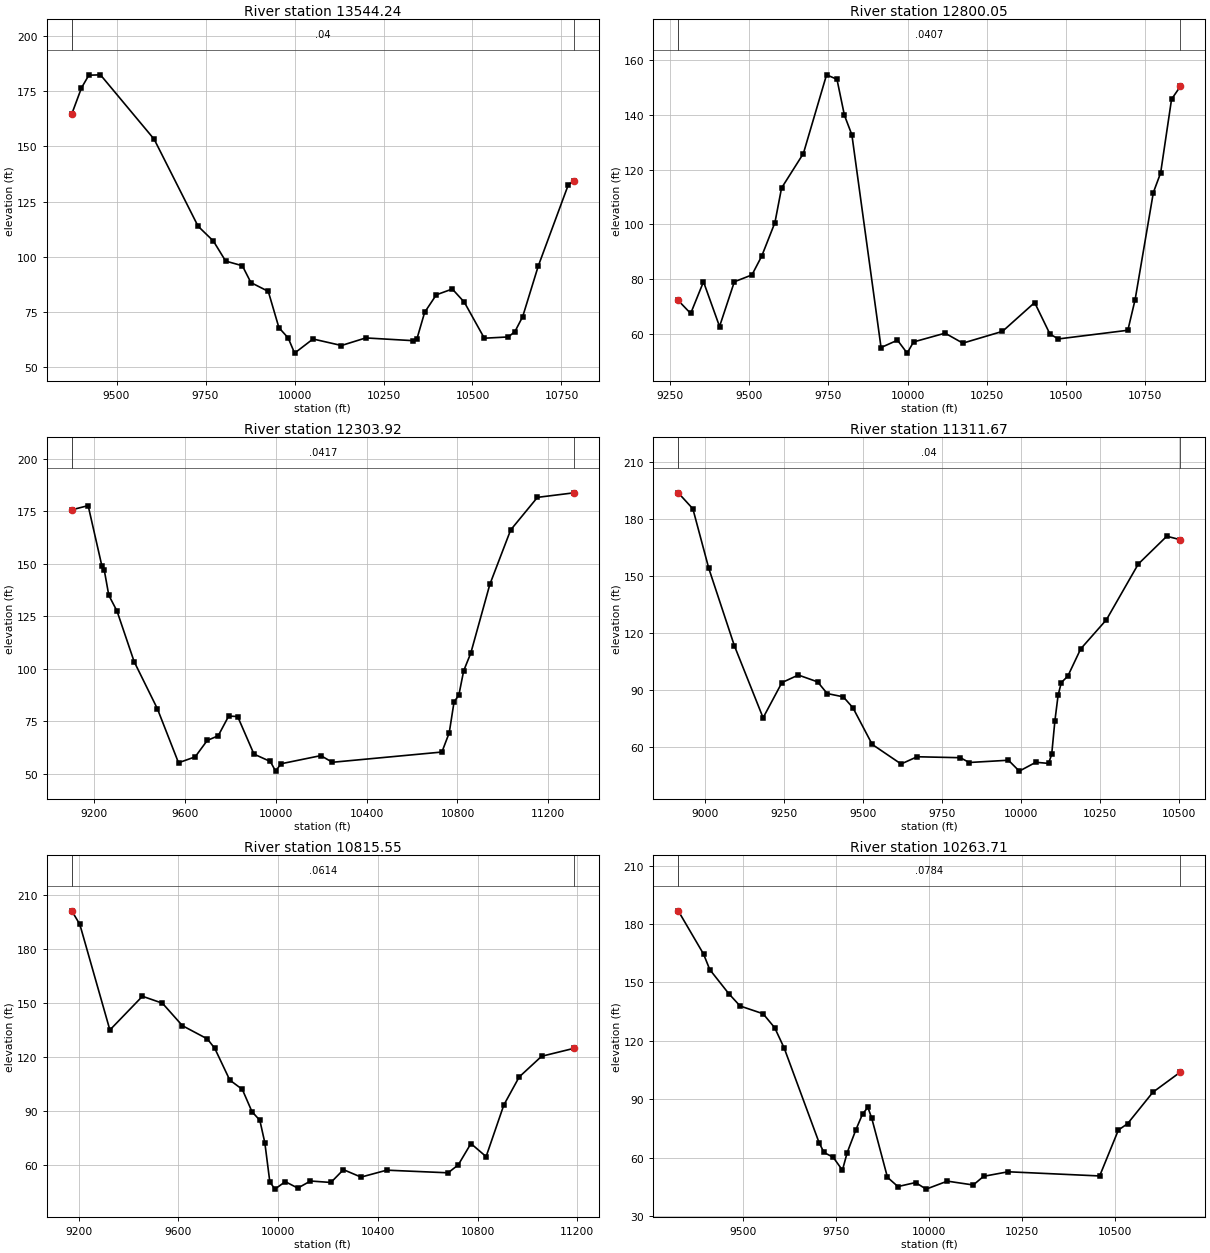
Type RM Length L Ch R = 1 ,13544.24,744.188800,744.188800,744.188800
XS GIS Cut Line= 6
424321.495455772814519.361403495424169.571416378814877.893934205
424030.582737923815088.683133975423949.848111302815182.910311967
423841.479733348815409.742272034424020.666667223815758.741008073
#Sta/Elev= 30
9374.159 164.7329401.466176.60679422.092182.34749454.718182.52019605.651153.2664
9729.043113.77059772.043107.04039806.50997.946229853.45195.828539877.41488.18583
9926.25484.189769956.12767.713229982.15663.0410610000.2156.1484410051.97 62.5675
 10131.959.6105510200.1363.0497310333.1261.8033710343.9662.6615110365.6474.67983
10398.3782.6324410443.3485.2616410477.0679.2703910533.2762.9242610600.7163.49881
10619.1165.9001110641.0172.7061510684.7995.6861810769.33132.638510784.78134.3648
#Mann= 3 , 0 , 0
9374.159    0.04       09374.159    0.04       010784.78    0.04       0
#XS Ineff= 2 , 0
       0                 10431.8       0
Bank Sta=9374.159,10784.78
Exp/Cntr=0.3,0.1

Type RM Length L Ch R = 1 ,12800.05,496.125800,496.125800,496.125800
XS GIS Cut Line= 6
423187.728295257814525.998172093423236.430630697814794.554635913
423313.534268305814993.169019389423408.199402731815111.970822158
423569.846866089815158.847743132423934.525053114815839.013578072
#Sta/Elev= 30
9276.47372.140329315.72467.378799356.14678.98427 9406.7962.608469453.43778.97783
9508.90281.48613 9539.8388.377099581.418100.6338 9602.33113.29199671.185125.9201
9744.259154.71649777.102153.09039800.638139.91979824.173132.75239916.14554.90992
9967.926 57.60019998.49952.8640210018.6156.9523210118.1260.1683710174.1256.52016
10299.1760.8298110400.5971.3680410448.8659.8404110475.3558.0557410694.5561.23119
10717.5472.4704210774.99 111.63710797.98118.819210832.45145.808610860.04150.4504
#Mann= 3 , 0 , 0
9276.473  0.0407       09276.473  0.0407       010860.04  0.0407       0
#XS Ineff= 2 , 0
       0                10394.46       0
Bank Sta=9276.473,10860.04
Exp/Cntr=0.3,0.1

Type RM Length L Ch R = 1 ,12303.92,992.251700,992.251700,992.251700
XS GIS Cut Line= 6
422887.155626077814533.365149284423087.373044647815255.698184907
423199.139346698815413.132945463423403.999561102815404.452174386
423652.141118256815563.946887464423921.774732062816267.226796963
#Sta/Elev= 30
9100.008175.72799172.173177.73039232.796148.97939242.922147.20639263.175135.0587
9299.558127.47739374.922103.43789477.28581.029169570.51255.289039643.95358.10638
9697.27365.940619745.29468.118419791.65977.527329831.19977.309899903.02759.40827
9975.15155.902389998.39651.3073410022.2954.8067310197.8858.6918110248.4855.51657
10731.45 60.399210763.7869.5998810784.9884.2611610806.1487.5156210827.3199.05411
10858.78107.512810942.65140.204711034.47166.145511152.48181.661711312.98183.8221
#Mann= 3 , 0 , 0
9100.008  0.0417       09100.008  0.0417       011312.98  0.0417       0
#XS Ineff= 2 , 0
       09846.276                       0
Bank Sta=9100.008,11312.98
Exp/Cntr=0.3,0.1

Type RM Length L Ch R = 1 ,11311.67,496.125900,496.125900,496.125900
XS GIS Cut Line= 6
422781.650283963814549.029895488422837.836977922814955.186008967
422917.468162669815402.488569069423021.322040066815643.928110528
422983.294625793815900.443134184422979.537503622816097.666144531
#Sta/Elev= 30
8916.212193.78128962.466185.37079012.774153.99639093.462113.35299184.39475.33902
9243.81493.88321 9295.7597.862599356.56394.264039387.00788.113459437.747 86.3857
 9468.1980.644619529.07861.355989620.40951.032049671.14954.839249807.90454.33882
9835.49451.814099959.65553.011169993.99347.2754610046.2151.9367910086.2951.34644
10096.34 56.053810106.3873.6517510116.5787.2118810126.7793.9073610147.1897.24512
   10188111.627310269.34126.9849   10370156.307810460.06170.930910502.78169.0984
#Mann= 3 , 0 , 0
8916.212    0.04       08916.212    0.04       010502.78    0.04       0
#XS Ineff= 2 , 0
       09701.912                       0
Bank Sta=8916.212,10502.78
Exp/Cntr=0.3,0.1

Type RM Length L Ch R = 1 ,10815.55,551.833700,551.833700,551.833700
XS GIS Cut Line= 6
422598.377166719814582.790732872422636.508581725815074.866828832
422618.143147443815346.211752484 422639.48742003815472.379889087
422609.257729863815694.815833493422778.374153816816572.771945586
#Sta/Elev= 30
9171.815201.37059204.176193.79459324.739135.0219 9455.35153.79539535.576149.9321
9615.688 137.4339715.709130.06739745.751124.76969805.957107.12549856.219101.9358
9894.95789.534719926.44684.74638  9946.572.257599966.60450.434999986.97546.41376
 10028.550.5730610078.8846.9937810129.7350.9327310211.6850.11913 10261.957.25532
10332.6353.11185 10435.756.9682610682.0755.4987310722.8559.9491610773.5871.79355
10834.4564.5074810905.4893.2348810967.26 108.87611057.26120.393811186.54124.7908
#Mann= 3 , 0 , 0
9171.815  0.0614       09171.815  0.0614       011186.54  0.0614       0
#XS Ineff= 2 , 0
       0                10262.11       0
Bank Sta=9171.815,11186.54
Exp/Cntr=0.3,0.1

Type RM Length L Ch R = 1 ,10263.71,571.537100,571.537100,571.537100
XS GIS Cut Line= 6
421945.740205288814891.014618874421992.166040242 815132.10142608
422053.890915781815268.769710422422321.300252914815546.192942068
422576.162658334815879.683110848422505.668801546816009.825615749
#Sta/Elev= 30
9326.231186.79519394.426164.53879411.056156.60639461.846144.32249492.463137.9263
9554.345133.93599585.637126.72659611.054116.31479704.77267.800799718.09862.68261
9742.703 60.25049767.64953.595249780.46862.621839803.88874.388399821.86682.48882
9836.10385.852969846.56780.210929888.71549.941789916.81345.180239964.23647.24621
 9992.7143.8666610049.6647.9704210119.3945.9971510147.3350.4535510213.2152.77796
10459.2150.6312510509.5574.2188110534.0877.4451810602.3193.6288310676.04103.9601
#Mann= 3 , 0 , 0
9326.231  0.0784       09326.231  0.0784       010676.04  0.0784       0
#XS Ineff= 2 , 0
       0                               0
Bank Sta=9326.231,10676.04
Exp/Cntr=0.3,0.1

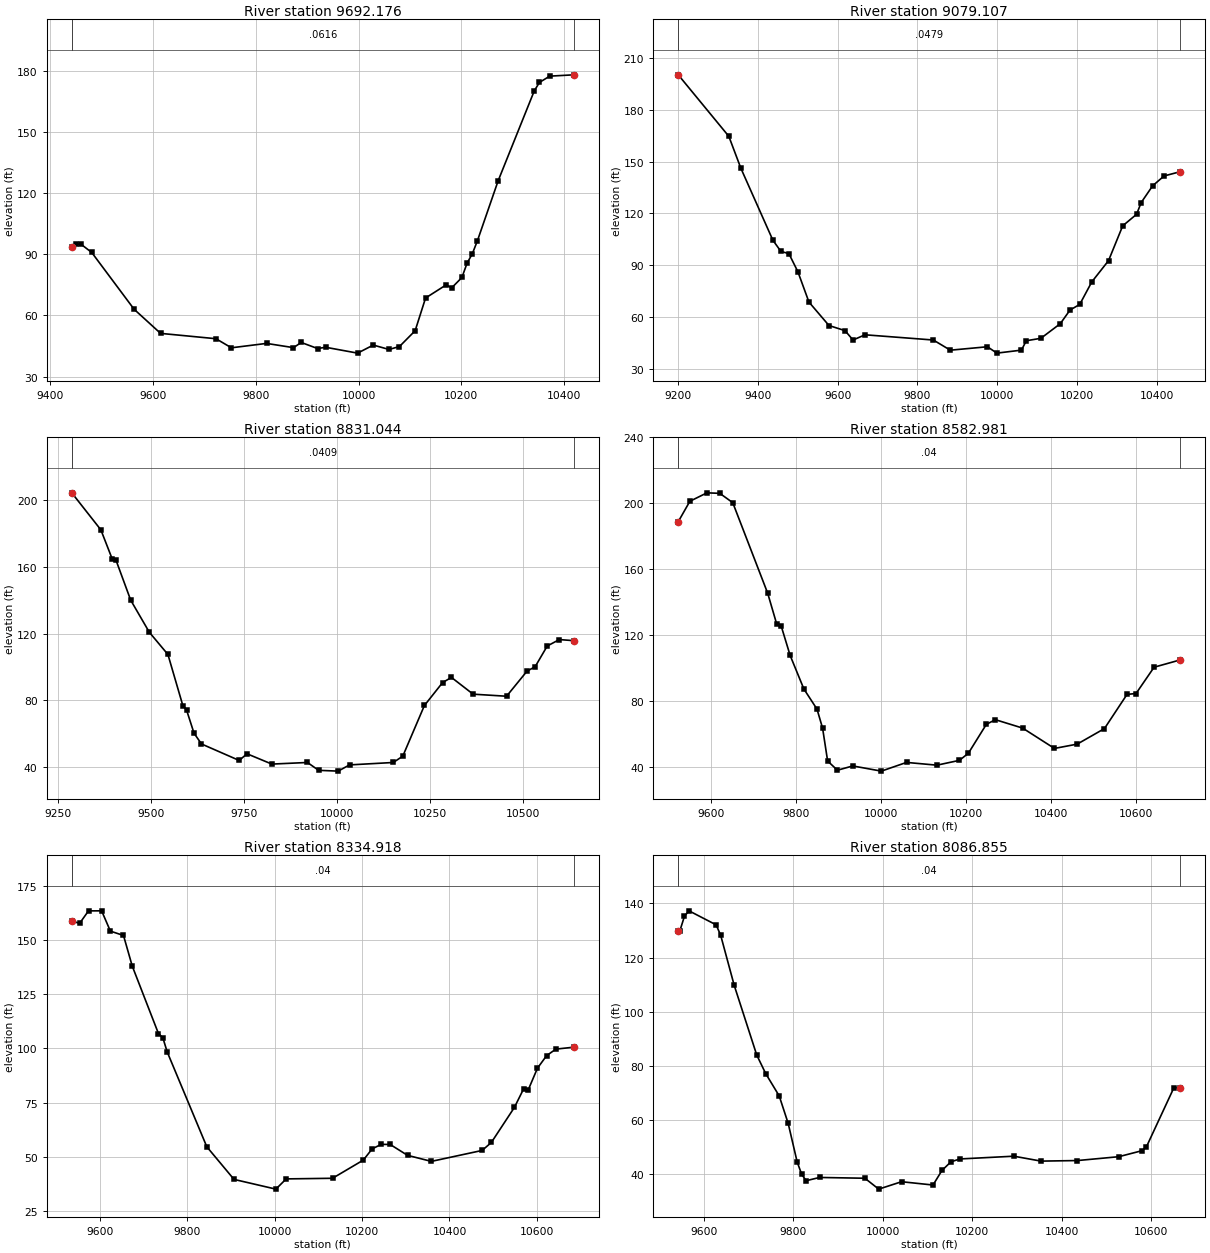
Type RM Length L Ch R = 1 ,9692.176,613.069700,613.069700,613.069700
XS GIS Cut Line= 6
422054.607813015815407.284372987 422120.86569561815673.116748389
422226.403071867815771.150684857422294.004448941815861.244220804
422334.445660621816071.757191151422356.478937528 816301.83493715
#Sta/Elev= 30
9441.85493.547089449.80695.118539460.11294.896489480.72490.894679563.17163.06545
9614.70151.23414 9722.53 48.61549752.59944.164219821.00246.315859873.39344.23818
9888.59146.768499920.23543.812959936.20144.41539 9998.2241.5500210028.7945.50164
10059.3543.3475510079.7244.7811110110.2752.5443810130.5368.5702410171.0275.07546
10181.15 73.499310201.3478.6443810211.42 85.727110221.4990.2118210231.5796.71221
10271.84126.061210342.15  170.1410352.19174.279310372.24177.357710419.18178.0011
#Mann= 3 , 0 , 0
9441.854  0.0616       09441.854  0.0616       010419.18  0.0616       0
#XS Ineff= 2 , 0
       0                               0
Bank Sta=9441.854,10419.18
Exp/Cntr=0.3,0.1

Type RM Length L Ch R = 1 ,9079.107,248.063000,248.063000,248.063000
XS GIS Cut Line= 6
421851.124606275814928.503818473421893.794378661815425.439231677
 421888.73678723 815555.42015089421853.834735158815638.375531941
421637.772592209815956.709903358421562.974746136816091.233549424
#Sta/Elev= 30
9200.381200.21719327.194164.59979357.269146.16779437.568 104.4569457.65897.97868
9477.74896.672749500.36986.144979527.97368.635439578.19855.043499618.37852.08704
9638.46846.656679668.60349.677789839.76546.654389882.39440.763659975.36342.74977
    999939.0608110060.6240.79701 10072.846.2348810109.3147.6430910158.0156.11543
10182.3564.00516 10206.767.2653410236.9680.3125810278.8592.6014110314.42 112.766
10349.18119.459510360.76126.251710389.54135.9832 10418.2141.665910458.81144.1242
#Mann= 3 , 0 , 0
9200.381  0.0479       09200.381  0.0479       010458.81  0.0479       0
#XS Ineff= 2 , 0
       0                10296.55       0
Bank Sta=9200.381,10458.81
Exp/Cntr=0.3,0.1

Type RM Length L Ch R = 1 ,8831.044,248.062900,248.062900,248.062900
XS GIS Cut Line= 6
421829.933658405814936.900231781 421803.35875178815439.060094259
421722.628602076815533.820773723421584.014848384815575.809808268
421462.935375357815678.588076375421276.146202552816041.340704139
#Sta/Elev= 30
9286.965 204.5839365.137182.33199395.165165.07299405.174164.46279445.211140.0858
9495.258120.78339545.277107.40939585.27776.719469595.27774.057969615.28660.13467
9635.33353.627689736.74243.703529757.60847.727859824.46741.521799920.12242.49158
9950.01337.7742610002.5637.2919210033.0941.0348910150.6142.4844810176.1746.29366
10234.2276.7472410283.2290.56219 10306.993.6122110365.0283.5522810454.87 82.3115
10509.85 97.388410531.65100.045110564.19112.506510596.68116.376110635.64115.7068
#Mann= 3 , 0 , 0
9286.965  0.0409       09286.965  0.0409       010635.64  0.0409       0
#XS Ineff= 2 , 0
       0                10289.29       0
Bank Sta=9286.965,10635.64
Exp/Cntr=0.3,0.1

Type RM Length L Ch R = 1 ,8582.981,248.062900,248.062900,248.062900
XS GIS Cut Line= 6
421640.015539362814957.705574037 421617.89793427815111.286642535
421579.638804448815233.568601264421513.254418152815351.293472377
421420.679681401815464.306018025421205.508182111816043.249839826
#Sta/Elev= 30
  9522.2188.74419549.591201.15419589.923206.28799620.191205.97349650.724200.3021
9733.115  145.279753.955126.89029764.617125.62359785.939107.56019818.32787.18291
9849.28874.937189862.445 63.37449874.31743.443219897.43637.859319933.59640.45288
   1000137.3050710060.2442.59403 10131.940.9221710184.8643.8409310206.0448.15015
10248.4165.7116910269.6768.5415910333.9463.4387910408.93 51.086710462.4953.69443
10526.7663.1375510579.9983.9001410601.2584.4342910643.76100.406310705.58104.8454
#Mann= 3 , 0 , 0
  9522.2    0.04       0  9522.2    0.04       010705.58    0.04       0
#XS Ineff= 2 , 0
       0                10332.53       0
Bank Sta=9522.2,10705.58
Exp/Cntr=0.3,0.1

Type RM Length L Ch R = 1 ,8334.918,248.063000,248.063000,248.063000
XS GIS Cut Line= 6
421219.455788179814946.814213496421224.867337553815258.554302851
421323.263240048815448.996295141421335.730036352815520.516470208
421304.204042726815686.149225614421182.969878316816043.858983172
#Sta/Elev= 30
9535.432158.67869553.683157.85539573.729163.52679603.773163.55459623.802154.1879
9653.834 152.1779673.835138.06549733.857106.89389743.868 104.9789753.87898.41755
9844.548 54.62159906.81339.5649810002.6535.0758610026.23 39.7986 10132.340.08303
10202.7548.4741810223.0353.6514610243.5855.7364510264.1855.70344 10304.150.66591
10358.5747.8843410474.7252.9327110495.8356.6036910548.6372.8089710569.7481.37362
 10580.3 80.902510601.4290.9196310622.5496.7398910643.6699.7147210684.69100.6045
#Mann= 3 , 0 , 0
9535.432    0.04       09535.432    0.04       010684.69    0.04       0
#XS Ineff= 2 , 0
       0                10305.24       0
Bank Sta=9535.432,10684.69
Exp/Cntr=0.3,0.1

Type RM Length L Ch R = 1 ,8086.855,248.062900,248.062900,248.062900
XS GIS Cut Line= 6
421080.861097026814941.157287325421051.654983878815258.297071759
421086.221125381815458.950357676421083.431436761815624.444308992
421053.529174901815823.473384705 421001.30826571816048.768756486
#Sta/Elev= 30
9543.411129.91689547.288 129.9819557.378135.28799567.468137.24819628.008132.0701
9638.098128.25849668.368109.73869718.69983.982819738.77277.11825 9768.8868.87909
9788.95258.710089808.99844.468499818.99839.958989828.99837.562689858.99838.76888
9960.18638.479439991.06834.4588910042.0837.19558 10112.335.97638 10132.341.36097
10152.3144.5419810172.3345.6028310292.78 46.6206 10353.544.8063310434.7745.01443
10527.0146.4350510578.3648.6317410588.6450.0190510650.3371.9797510664.4871.76617
#Mann= 3 , 0 , 0
9543.411    0.04       09543.411    0.04       010664.48    0.04       0
#XS Ineff= 2 , 0
       0                10226.16       0
Bank Sta=9543.411,10664.48
Exp/Cntr=0.3,0.1

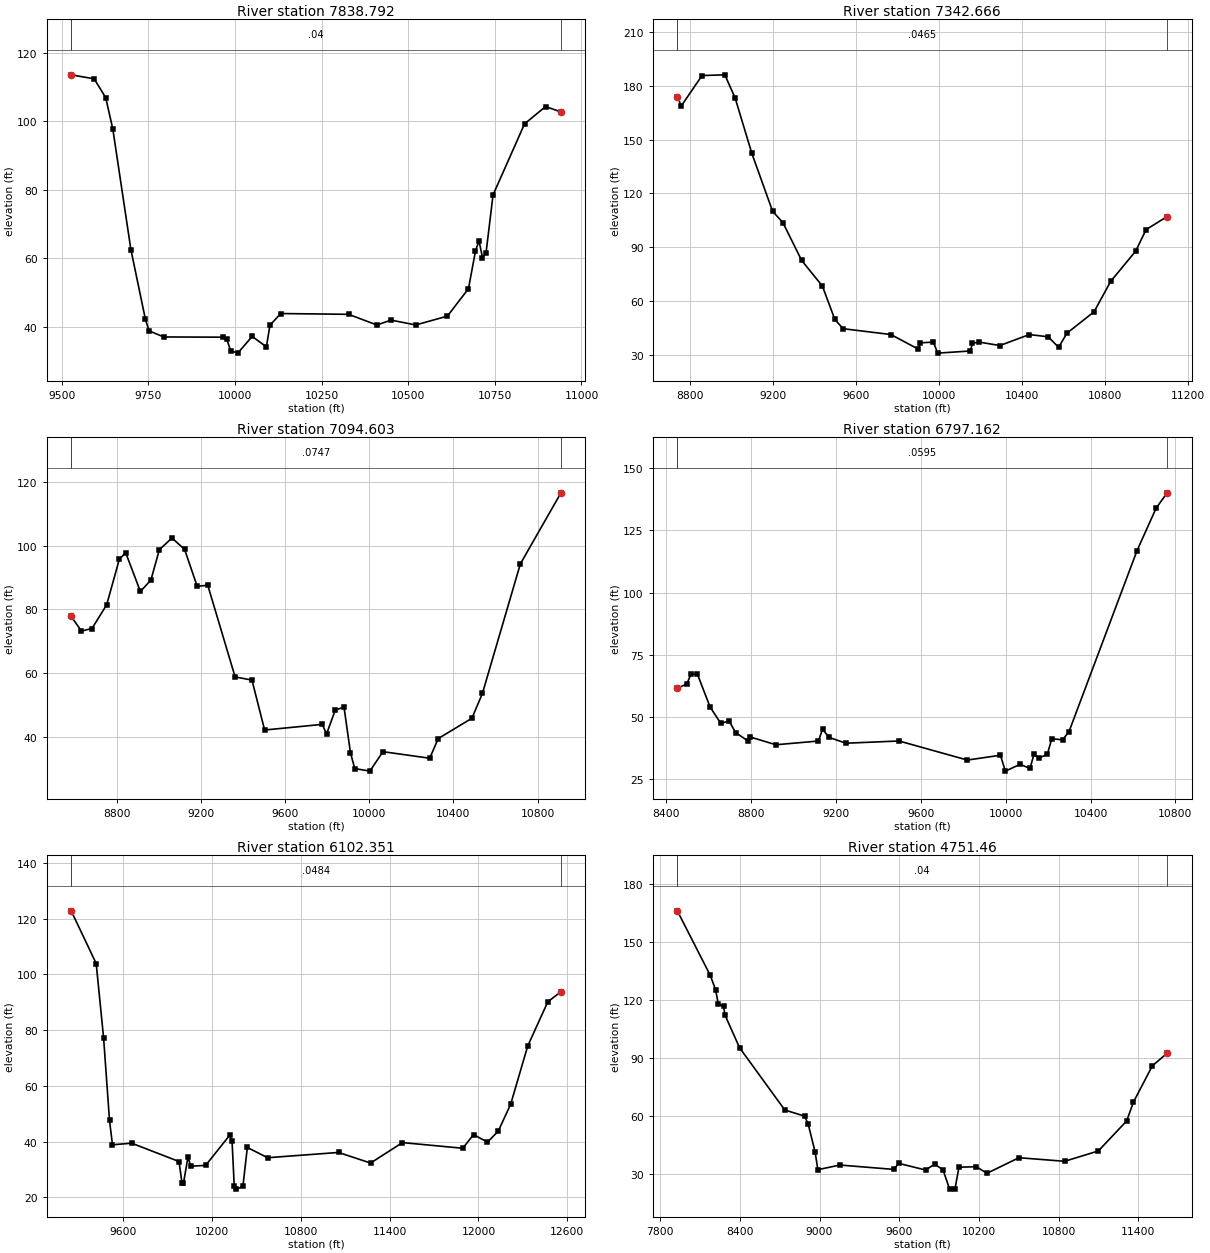
Type RM Length L Ch R = 1 ,7838.792,496.125800,496.125800,496.125800
XS GIS Cut Line= 6
420999.070786385814937.818907298 420944.12531241815148.182666333
420851.404470901815394.585008276420785.786964062815659.040280438
420725.996291331815954.663894645420671.948694494816308.995162145
#Sta/Elev= 30
9527.384113.57369593.858112.40259627.062106.91119647.66797.692759699.82562.48284
9741.626 42.16589752.18738.781499794.64336.994849966.08536.929169976.71536.28534
9987.344 33.013710008.2732.2718710049.7137.1477710090.7534.1203510101.0740.40755
10132.0543.8345910327.8743.6097310409.7140.4908210450.4341.9140610521.6840.50423
10613.1443.0822510673.9251.0890110694.1762.09119 10704.365.0700410714.4360.20201
10724.5661.4611710744.8278.4802910835.8699.2623310896.44104.299410940.86102.7335
#Mann= 3 , 0 , 0
9527.384    0.04       09527.384    0.04       010940.86    0.04       0
#XS Ineff= 2 , 0
       0                10168.38       0
Bank Sta=9527.384,10940.86
Exp/Cntr=0.3,0.1

Type RM Length L Ch R = 1 ,7342.666,248.063000,248.063000,248.063000
XS GIS Cut Line= 6
420487.322360538813885.896190756420471.291903781814822.370115328
420493.279684175 815031.77426419420566.492167635815276.371575469
420504.601731986815661.345258206420456.676538193816226.264925972
#Sta/Elev= 30
8736.691174.09168755.796168.84888855.813185.81528965.847186.21569015.863173.1373
9095.887142.40639195.918110.10879245.933103.68449335.96182.648799435.99268.34166
    949649.698749536.00144.536039766.21841.286239897.78433.17576 9908.08 36.6434
9970.86137.059169992.254  30.90410149.46 32.100610159.4836.40167 10189.737.10764
10291.4435.14102 10433.741.26564 10524.640.0190910574.8834.1451310615.0742.03905
10745.6753.9641910825.9270.9684110946.2987.8154210996.4599.8198111097.99107.1351
#Mann= 3 , 0 , 0
8736.691  0.0465       08736.691  0.0465       011097.99  0.0465       0
#XS Ineff= 2 , 0
       09918.659        10461.34       0
Bank Sta=8736.691,11097.99
Exp/Cntr=0.3,0.1

Type RM Length L Ch R = 1 ,7094.603,297.441700,297.441700,297.441700
XS GIS Cut Line= 6
420283.397179408813866.161495808420273.820968276814674.243817457
420356.194216269815200.744441545420329.587356997815349.336641921
420368.489222491815659.121911166 420359.04679804816177.860264889
#Sta/Elev= 30
8584.44877.766578633.28773.165628683.28873.959538753.29381.422168813.30295.70351
8843.30697.772688913.31585.588168963.32289.161029003.32898.672459063.336102.3547
9123.34498.784929183.35287.173519233.35987.557369363.37158.771299443.399 57.7877
9503.50142.123739777.21743.886369797.92440.907729839.33948.419729880.75549.28108
9911.38234.973689931.63430.0300910003.6529.2247910065.5635.33031 10287.9  33.268
10328.11 39.4335 10488.345.81313 10538.353.6262210718.3694.2270710911.34116.5302
#Mann= 3 , 0 , 0
8584.448  0.0747       08584.448  0.0747       010911.34  0.0747       0
#XS Ineff= 2 , 0
       09824.469        10402.38       0
Bank Sta=8584.448,10911.34
Exp/Cntr=0.3,0.1

Type RM Length L Ch R = 1 ,6797.162,694.810000,694.810000,694.810000
XS GIS Cut Line= 6
420016.930314822813840.374379881419999.389513561815075.892804659
420032.564431319815239.980093086420137.967416325815429.462128304
 420187.66960808815573.532738117420215.739108158  816106.8085531
#Sta/Elev= 30
8452.29461.480338496.92163.130918516.92267.161498546.92467.117148606.92653.84437
8656.92847.332838696.92948.19242 8726.9343.580038786.93340.122088796.93541.76857
8916.97338.670739117.07840.167219137.09144.953889167.111 41.64979247.16339.29256
9497.27240.189699819.38232.505839975.36334.447859998.53528.0470110068.0530.78202
10114.7929.1198910133.8235.0101410154.9533.2419610196.58 34.823510217.2241.13025
10268.1340.6388110298.5743.97844 10619.2116.900910709.21133.984710761.02140.1628
#Mann= 3 , 0 , 0
8452.294  0.0595       08452.294  0.0595       010761.02  0.0595       0
#XS Ineff= 2 , 0
       09590.005                       0
Bank Sta=8452.294,10761.02
Exp/Cntr=0.3,0.1

Type RM Length L Ch R = 1 ,6102.351,1350.891600,1350.891600,1350.891600
XS GIS Cut Line= 4
419537.187375665814375.753416821 419530.06776765 815412.19521603
 418842.56776765 816146.57021603418472.776101023817360.111882702
#Sta/Elev= 30
9246.794 122.7849416.044103.89189466.04577.229789506.046 47.62869526.047  38.871
 9656.0539.442139976.05732.861889996.05825.0719410006.0625.1023210036.0634.33911
10056.0631.1825710156.0631.4864310319.9442.3885910334.5740.08186 10349.224.07577
10363.8422.9658310407.7323.9364310437.7837.9134610574.7634.23089 11054.236.11761
11271.0332.3228611486.2139.6565711893.9137.6226411967.09 42.531912061.1839.79953
12134.3543.8147612217.99 53.425412332.9874.2719212468.8890.1400512557.86 93.7849
#Mann= 3 , 0 , 0
9246.794  0.0484       09246.794  0.0484       012557.86  0.0484       0
#XS Ineff= 2 , 0
       09771.094        10257.31       0
Bank Sta=9246.794,12557.86
Exp/Cntr=0.3,0.1

Type RM Length L Ch R = 1 , 4751.46,1019.239600,1019.239600,1019.239600
XS GIS Cut Line= 6
 418905.06776765813776.778549343 418920.69276765814313.236882672
419024.859434336814683.028549358418868.609434336815255.945216015
 418655.06776765815641.361882672 418420.69276765817354.903549343
#Sta/Elev= 30
7929.639166.22858177.966132.71648217.983 125.2368237.991117.89398278.008116.6637
8288.012112.25348398.059 95.28078738.27563.013358887.97959.792778914.74355.59928
8966.56941.248038987.29932.053989153.14334.464819557.592 32.21119596.23435.34258
 9797.6731.885149866.26434.89399 9928.78 32.06359978.97821.9815810019.1421.98269
10049.2533.3472110179.7733.5938110260.0930.1965610501.0438.2624510844.5536.40631
11098.3441.7733411311.5357.3273411362.2967.0480811504.4185.8629911615.98 92.4481
#Mann= 3 , 0 , 0
7929.639    0.04       07929.639    0.04       011615.98    0.04       0
#XS Ineff= 2 , 0
       0                10467.71       0
Bank Sta=7929.639,11615.98
Exp/Cntr=0.3,0.1

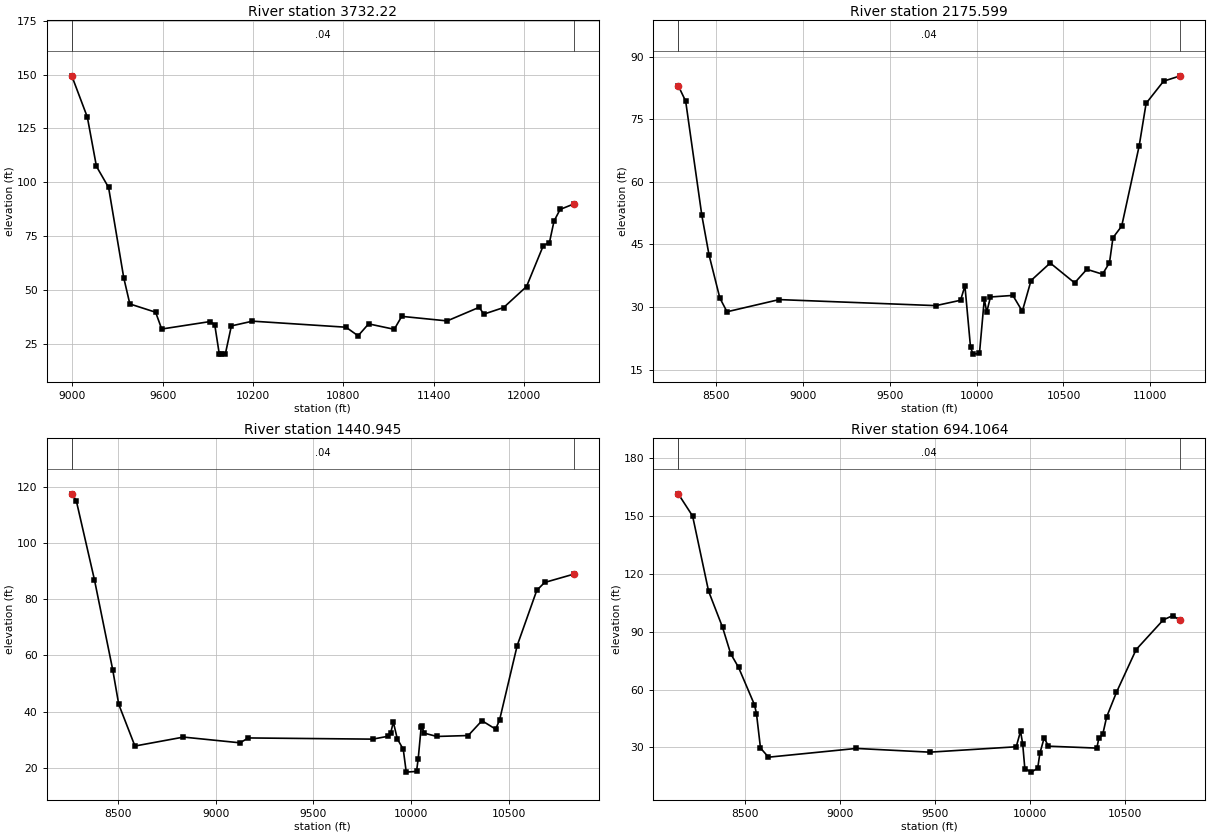
Type RM Length L Ch R = 1 , 3732.22,1556.621400,1556.621400,1556.621400
XS GIS Cut Line= 5
 418295.69276768814042.403549343 418405.06776765814917.403549343
418462.359434366815750.736882687418462.359434366816422.611882672
418306.109434336817354.903549343
#Sta/Elev= 30
8996.924149.39339100.318130.24159160.785107.40029241.40897.627359342.18655.72304
9382.49743.61495 9553.8239.765439594.132 31.98049916.41835.454289946.48933.90964
 9976.5620.396739986.58320.3411710016.6520.3411710056.7533.4239510197.0835.62839
 10818.332.81891 10898.328.83398 10968.3 34.3735 11138.3 31.8537 11188.337.85471
11489.7235.7430911702.6542.0616311733.0738.8730711864.8841.9375512016.9851.68514
12128.5170.6875212169.07 72.060512199.4982.0222712240.0587.43959 12331.289.98678
#Mann= 3 , 0 , 0
8996.924    0.04       08996.924    0.04       0 12331.2    0.04       0
#XS Ineff= 2 , 0
       0                11158.66       0
Bank Sta=8996.924,12331.2
Exp/Cntr=0.3,0.1

Type RM Length L Ch R = 1 ,2175.599,734.653800,734.653800,734.653800
XS GIS Cut Line= 4
 417295.69276765814573.653549358 417655.06776765815922.611882687
 418030.06776765816308.028549343417946.734434336817261.153549343
#Sta/Elev= 30
8282.08583.047098324.87379.348258418.01251.943688459.408 42.4742  8521.532.15834
8562.89528.85582 8863.0131.773049765.13930.328269907.434 31.61299932.56735.05923
9964.79420.379349979.13418.7007510016.2818.8758410044.1931.9215410058.1428.75537
10079.5132.3991410208.57 32.775310262.9928.9736310313.1836.34629 10423.640.54756
10564.13 35.7819 10634.439.0345210724.74 37.8632 10764.940.6271710784.9746.61312
10835.1649.3960210935.5568.57983 10975.778.8167911076.0884.12775 11172.685.41732
#Mann= 3 , 0 , 0
8282.085    0.04       08282.085    0.04       0 11172.6    0.04       0
#XS Ineff= 2 , 0
       0                               0
Bank Sta=8282.085,11172.6
Exp/Cntr=0.3,0.1

Type RM Length L Ch R = 1 ,1440.945,746.838700,746.838700,746.838700
XS GIS Cut Line= 4
 417076.94276768 814552.82021603417446.734434366815922.611882687
 417155.06776768816261.153549343417102.984434336816964.278549358
#Sta/Elev= 30
8263.204117.68538286.178115.2789  8379.486.978848472.62154.992758503.69542.55768
8586.55927.685848835.15130.876699125.17528.829059166.60730.57204 9803.9830.14545
 9883.8631.183519896.37632.353839909.57536.268289929.82230.274849960.46426.52744
9975.78418.3726710028.3718.6320110037.0723.1570510052.3934.5783810054.7734.67858
10067.9732.2850910132.7531.1005110293.1831.4319810363.38 36.726410433.5733.71004
10453.62 36.981210543.8763.5332510644.1483.2422810684.2586.0500810833.9489.03255
#Mann= 3 , 0 , 0
8263.204    0.04       08263.204    0.04       010833.94    0.04       0
#XS Ineff= 2 , 0
       0                               0
Bank Sta=8263.204,10833.94
Exp/Cntr=0.3,0.1

Type RM Length L Ch R = 1 ,694.1064,0.000000,0.000000,0.000000
XS GIS Cut Line= 6
416868.609434336814433.028549358416543.211927503815455.159541339
416536.357728779816034.339339316416707.151101053816360.111882672
 416826.94276765 816818.44521603416821.734434336816964.278549358
#Sta/Elev= 30
8150.908  161.328226.439149.82178310.395110.92018383.85692.232698426.52878.57158
8467.81371.504328551.76952.094998562.26347.475578583.25229.74342 8625.2324.97902
9086.98929.511339473.44327.579379927.75230.370669950.33438.421659961.62531.91887
9972.91619.0730410006.7917.2456510040.6619.2907510051.95 26.988410074.5334.94129
10097.12 30.6777 10351.429.6867110361.7334.66959 10382.436.7505410403.0845.83014
10454.7658.5924810558.1280.6956810700.9596.0761210750.9998.2731610790.2995.75251
#Mann= 3 , 0 , 0
8150.908    0.04       08150.908    0.04       010790.29    0.04       0
#XS Ineff= 2 , 0
       0                 10078.6       0
Bank Sta=8150.908,10790.29
Exp/Cntr=0.3,0.1